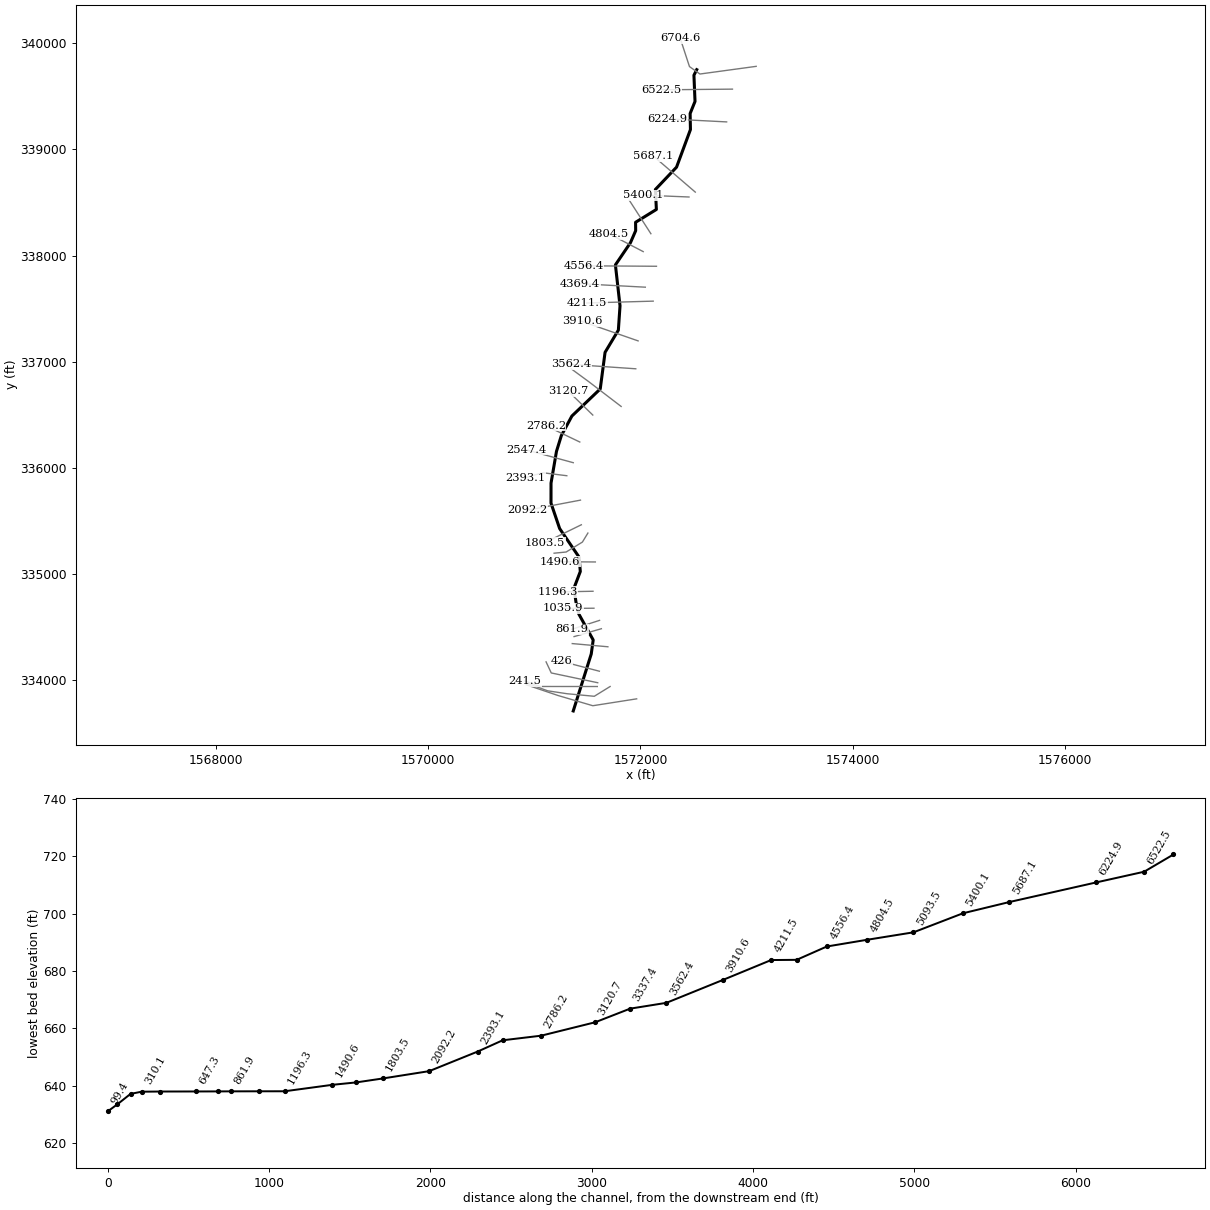
--- OLDFORK.prj (project) ---

Proj Title=OLDFORK
Current Plan=p01
Default Exp/Contr=0,0
English Units
Geom File=g01
Flow File=f01
Plan File=p01
BEGIN DESCRIPTION:
END DESCRIPTION:
DSS File=dss
DSS Export Rating Curves= 0
DSS Export Rating Curve Sorted= 0
DSS Export Volume Flow Curves= 0
DXF OffsetX= 0
DXF OffsetY= 0
DXF ScaleX= 0
DXF ScaleY= 0

--- OLDFORK.p01 (plan) ---

Plan Title=Floodplain
Program Version=4.00
Short Identifier=Floodplain
Geom File=g01
Flow File=f01
Subcritical Flow
K Sum by GR= 0
Std Step Tol= 0.01
Critical Tol= 0.01
Num of Std Step Trials= 20
Max Error Tol= 0.3
Flow Tol Ratio= 0.001
Split Flow NTrial= 30
Split Flow Tol= 0.02
Split Flow Ratio= 0.02
Log Output Level= 0
Friction Slope Method= 1
Unsteady Friction Slope Method= 2
Unsteady Bridges Friction Slope Method= 1
Parabolic Critical Depth
Global Vel Dist= 0 , 0 , 0
Global Log Level= 0
CheckData=True
Encroach Param=-1 ,0,0, 0
Run HTab= 0
Run UNet= 0
Run PostProcess= 0
Run WQNet= 0
UNET Theta= 0
UNET Theta Warmup= 0
UNET ZTol= 0
UNET ZSATol= 0
UNET MxIter= 0
UNET MaxInSteps= 0
UNET DtIC= 0
UNET DtMin= 0
UNET MaxCRTS= 0
UNET WFStab= 0
UNET SFStab= 0
UNET WFX= 1
UNET SFX= 1
UNET DSS MLevel= 1
UNET DZMax Abort= 0
UNET Convert EG Bridges= 0
UNET Use Existing IB Tables= 0
UNET Froude Reduction=False
UNET Froude Limit= 0
UNET Froude Power= 0
UNET Time Slicing=0,0, 5
DSS File=dss
Write IC File= 0
Echo Input=False
Echo Output=False
Write Detailed= 0
Detailed Automatic Start=False, 0
WQ ULTIMATE=-1
WQ Max Comp Step=1HOUR
WQ Output Interval=15MIN
WQ Output Selected Increments= 0
WQ Output face flow=0
WQ Output face velocity=0
WQ Output face area=0
WQ Output face dispersion=0
WQ Output cell volume=0
WQ Output cell surface area=0
WQ Output cell continuity=0
WQ Output face conc=0
WQ Output face dconc_dx=0
WQ Output face courant=0
WQ Output face peclet=0
WQ Output face adv mass=0
WQ Output face disp mass=0
WQ Output cell mass=0
WQ Output cell source sink temp=0
WQ Output cell source sink nsm=0
WQ Output MaxMinRange=-1
WQ Daily Max Min Mean=-1
WQ Daily Range=0
WQ Daily Time=0
WQ Create Restart=0
WQ Fixed Restart=0
WQ System Summary=False
Sorting and Armoring Iterations= 10
XS Update Threshold= 0.02
Hydraulics Update Threshold= 0.02
Energy Slope Method= 1
Volume Change Method= 0
XS Weighting Method= 0
Number of US Weighted Cross Sections= 1
Number of DS Weighted Cross Sections= 1
Upstream XS Weight=0.25
Main XS Weight=0.5
Downstream XS Weight=0.25
Number of DS XS's Weighted with US Boundary= 1
Upstream Boundary Weight= 1
Weight of XSs Associated with US Boundary= 0
Number of US XS's Weighted with DS Boundary= 1
Downstream Boundary Weight= 0.5
Weight of XSs Associated with DS Boundary= 0.5
Sediment Output Level= 4
Mass or Volume Output= 0
Output Increment Type= 1
Profile and TS Output Increment= 10
XS Output Flag= 0
XS Output Increment= 10
Disregard all LS=0
Disregard all Conn=0
Disregard all Breaches=0
Disregard all Pumps=0

--- OLDFORK.f01 (steady flow) ---

Flow Title=NFF Regression Equation
Program Version=4.00
Number of Profiles= 1
Profile Names=P100yr
River Rch & RM=OLDFORK,Main            ,6704.6
357.6627
River Rch & RM=OLDFORK,Main            ,6224.9
360.3189
River Rch & RM=OLDFORK,Main            ,5093.5
399.4256
River Rch & RM=OLDFORK,Main            ,4804.5
452.1448
River Rch & RM=OLDFORK,Main            ,2393.1
476.5351
River Rch & RM=OLDFORK,Main            ,2092.2
574.8735
River Rch & RM=OLDFORK,Main            ,1490.6
579.4121
River Rch & RM=OLDFORK,Main            ,1196.3
695.8123
Boundary for River Rch & Prof#=OLDFORK,Main            , 1
Up Type= 0
Dn Type= 3
Dn Slope=0.005
DSS Import GetInterval= 0
DSS Import GetPeak= 0
DSS Import FillOption= 0

--- OLDFORK.g01 (geometry) ---

Geom Title=Geometry
Program Version=4.00

River Reach=OLDFORK         ,Main
Reach XY= 30
     1572530.982      339752.531     1572504.531      339700.056
     1572514.777      339453.414     1572468.661       339338.93
     1572471.597      339187.744     1572340.591      338833.516
     1572141.226      338623.303     1572150.325      338434.585
     1571954.313      338313.783     1571955.083      338234.445
     1571905.924      338121.269     1571764.072      337912.074
     1571807.523      337525.863     1571791.888      337296.794
     1571666.521      337087.547     1571620.965      336742.379
     1571353.637      336487.134     1571254.418      336303.324
     1571208.381      336154.122      1571156.97      335854.778
     1571156.685      335666.323     1571238.147       335426.41
     1571421.279       335157.21     1571433.049      335021.567
     1571373.304       334864.52     1571392.199      334733.166
      1571418.26      334621.792      1571554.54      334376.059
     1571536.178      334243.733     1571366.506      333706.761

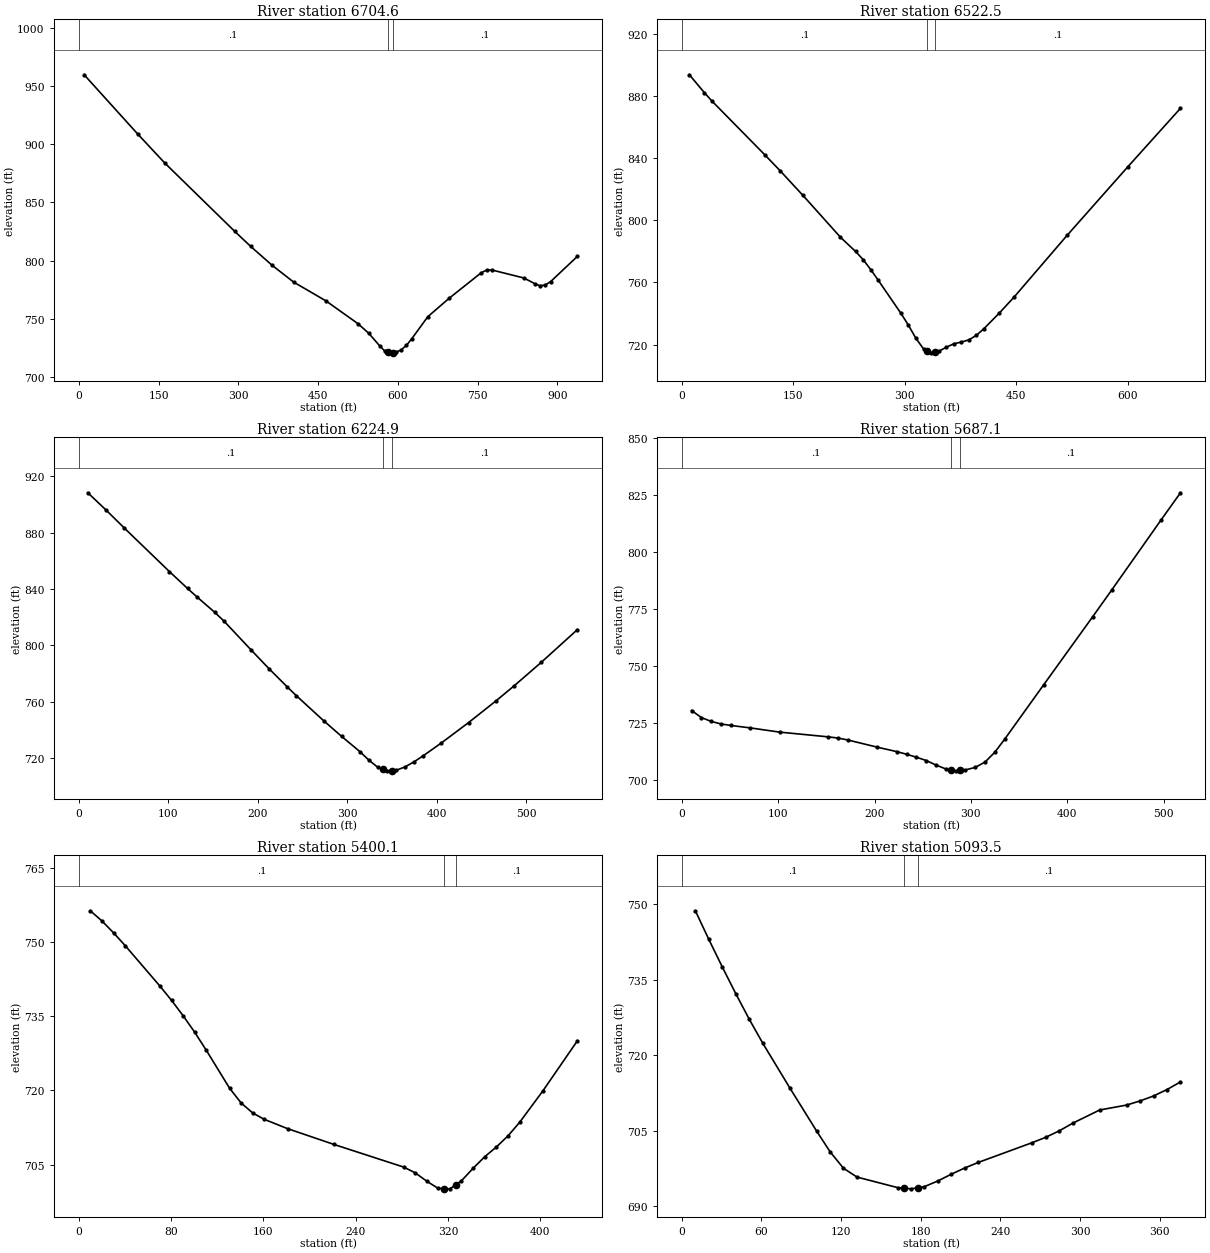
Type RM Length L Ch R = 1 ,6704.6  ,167,182,197.9
XS GIS Cut Line= 4
     1573091.462      339783.872     1572561.097      339711.549
     1572462.475       339781.68     1572374.812      340049.054
#Sta/Elev= 30
    10.1  959.61   111.1  908.56   161.6  883.83   292.9   825.2   323.2  812.15
   363.6  795.87     404  781.48   464.6  765.37   525.2  745.66   545.4  737.42
   565.5  726.84   575.6  722.11   580.7  721.39   585.7  720.68   590.7  720.91
   595.8  721.15   605.9  723.13   615.9     727     626   732.7   656.3  751.73
   696.5  767.61   756.8   789.5   766.8  791.78   776.9  791.86   837.2  784.97
   857.3  780.13   867.3   778.3   877.4  779.02   887.4  781.94   937.7  803.63
#Mann= 3 , 0 , 0
       0      .1       0   580.7    .045       0   590.7      .1       0
Bank Sta=580.7,590.7
XS Rating Curve= 0 ,0
Exp/Cntr=0.3,0.1

Type RM Length L Ch R = 1 ,6522.5  ,299.3,297.7,296.1
XS GIS Cut Line= 2
     1572867.919      339569.096     1572197.293      339562.521
#Sta/Elev= 30
    10.2  893.65    30.5  882.05    40.6   876.7   111.8  842.04   132.1  831.94
   162.6  816.16   213.4  789.05   233.7  779.91   243.9  774.66     254  768.29
   264.2  761.37   294.7   740.1   304.8   732.4     315   723.9   325.2  717.12
   330.3  715.87   335.3  714.65   340.3  715.14   345.5  715.65   355.7  718.25
   365.8  720.47     376  721.58   386.1     723   396.3  725.95   406.5   730.3
   426.8  740.12   447.1  750.66   518.2  790.27   599.5  834.21   670.7  872.07
#Mann= 3 , 0 , 0
       0      .1       0   330.3    .045       0   340.3      .1       0
Bank Sta=330.3,340.3
XS Rating Curve= 0 ,0
Exp/Cntr=0.3,0.1

Type RM Length L Ch R = 1 ,6224.9  ,554.7,537.7,536.5
XS GIS Cut Line= 2
      1572813.13      339260.081     1572256.466      339288.572
#Sta/Elev= 30
    10.1  908.24    30.4  896.04    50.7  883.33   101.3  852.33   121.6  840.32
   131.7  834.55     152   823.4   162.2  817.24   192.6  796.71   212.8  783.28
   233.1  770.43   243.2  764.23   273.6  746.53   293.9   735.3   314.2  724.55
   324.3   718.5   334.4  713.31   339.6  712.09   344.6  710.91   349.6  711.09
   354.7  711.28   364.8  713.73     375  717.42   385.1  721.64   405.4  730.75
   435.8  745.21   466.2  760.49   486.5  771.16   516.9  787.88   557.4  811.16
#Mann= 3 , 0 , 0
       0      .1       0   339.6    .045       0   349.6      .1       0
Bank Sta=339.6,349.6
XS Rating Curve= 0 ,0
Exp/Cntr=0.3,0.1

Type RM Length L Ch R = 1 ,5687.1  ,270,287,304.1
XS GIS Cut Line= 2
     1572517.265      338598.221      1572124.97      338935.726
#Sta/Elev= 30
    10.1  730.54    20.3  727.47    30.4  725.76    40.6  724.65    50.7  723.99
      71  722.91   101.5  721.06   152.2  718.97   162.4  718.44   172.5  717.58
   202.9  714.45   223.2  712.49   233.4  711.33   243.5  710.04   253.7  708.59
   263.8  706.61     274  704.89   279.1  704.48   284.1  704.07   289.1  704.27
   294.3  704.48   304.4  705.56   314.6   707.9   324.7  712.18   334.9  717.87
   375.4  741.75   426.2  771.57   446.5  783.63   497.2  814.06   517.5  826.07
#Mann= 3 , 0 , 0
       0      .1       0   279.1    .045       0   289.1      .1       0
Bank Sta=279.1,289.1
XS Rating Curve= 0 ,0
Exp/Cntr=0.3,0.1

Type RM Length L Ch R = 1 ,5400.1  ,332,306.6,281.1
XS GIS Cut Line= 2
     1572458.092      338552.197     1572026.349       338569.73
#Sta/Elev= 30
      10  756.27    20.1  754.21    30.1  751.83    40.2  749.24    70.3  741.07
    80.4  738.18    90.4  735.09   100.5  731.74   110.5  728.11   130.6  720.48
   140.7  717.47   150.7  715.46   160.8  714.17   180.9   712.3   221.1  709.11
   281.4  704.55   291.4   703.4   301.5   701.7   311.5  700.22   316.6  700.19
   321.6  700.15   326.6  700.96   331.6  701.78   341.7   704.3   351.7  706.62
   361.8  708.59   371.8  710.81   381.9  713.54     402  719.87   432.1  730.05
#Mann= 3 , 0 , 0
       0      .1       0   316.6    .045       0   326.6      .1       0
Bank Sta=316.6,326.6
XS Rating Curve= 0 ,0
Exp/Cntr=0.3,0.1

Type RM Length L Ch R = 1 ,5093.5  ,275.1,289,312.2
XS GIS Cut Line= 2
     1572098.671      338205.926     1571894.853      338521.515
#Sta/Elev= 30
    10.2  748.63    20.3  742.98    30.5  737.49    40.6  732.22    50.8  727.13
    60.9  722.41    81.2  713.58   101.5  704.98   111.7  700.85   121.8  697.58
     132  695.83   162.5  693.75   167.6  693.62   172.6   693.5   177.6  693.71
   182.8  693.94   192.9  695.06   203.1  696.41   213.2  697.64   223.4  698.74
     264  702.66   274.1  703.71   284.3  704.99   294.5  706.51   314.8  709.13
   335.1  710.11   345.2  710.93   355.4  711.91   365.5  713.18   375.7   714.7
#Mann= 3 , 0 , 0
       0      .1       0   167.6    .045       0   177.6      .1       0
Bank Sta=167.6,177.6
XS Rating Curve= 0 ,0
Exp/Cntr=0.3,0.1

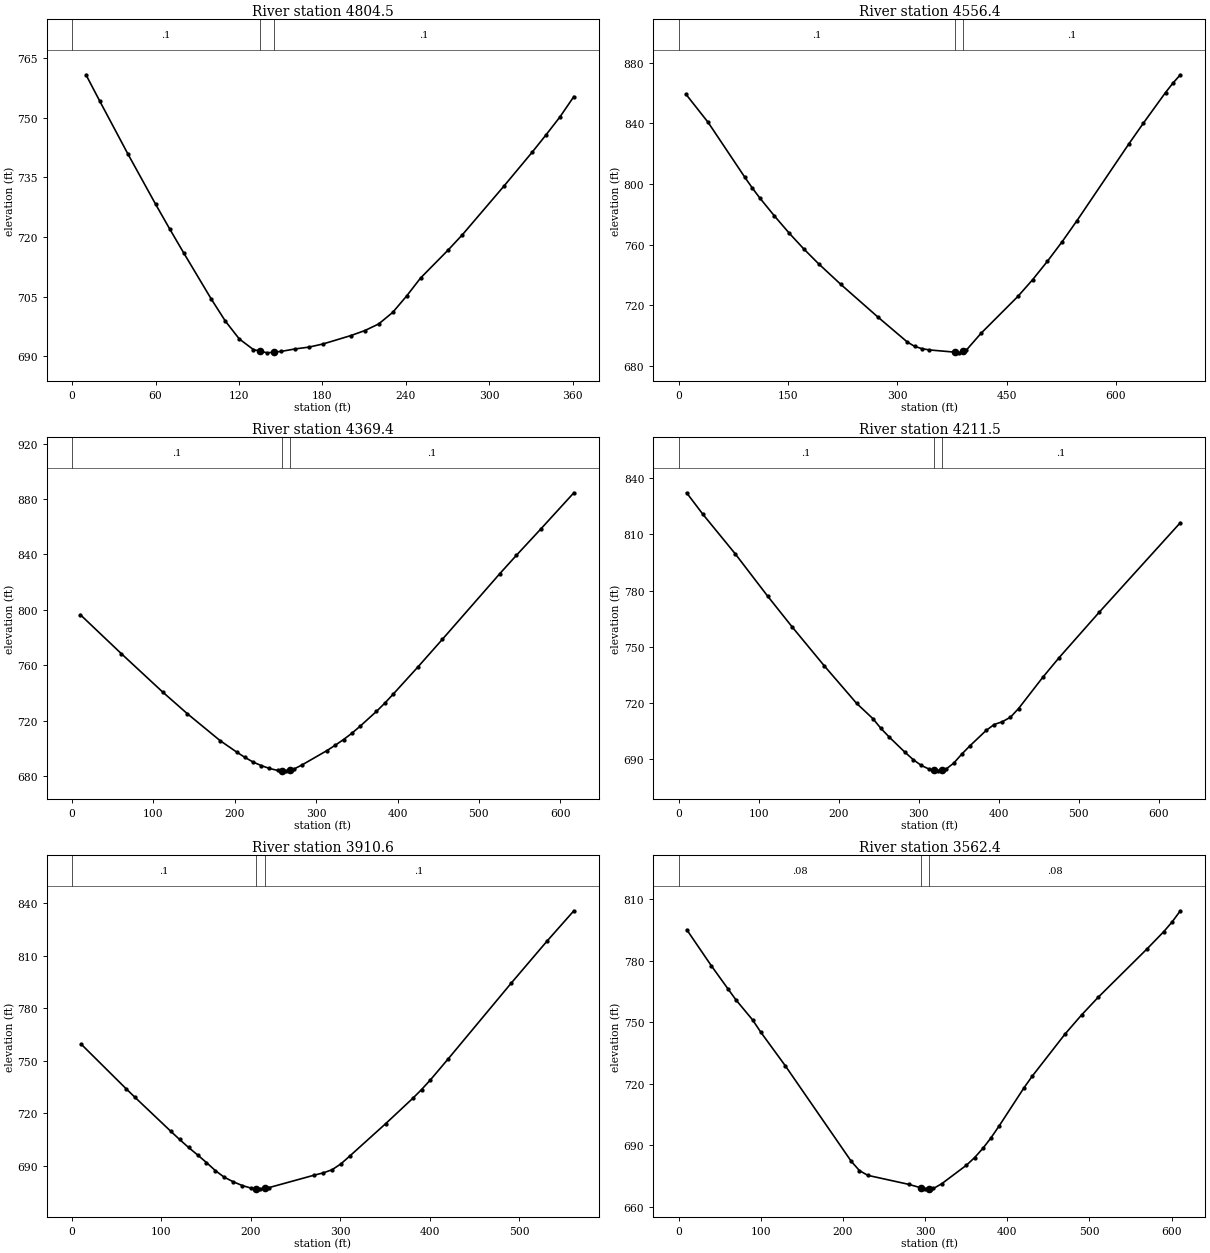
Type RM Length L Ch R = 1 ,4804.5  ,236.1,248.1,260
XS GIS Cut Line= 2
     1572026.349      338037.174     1571706.376      338203.735
#Sta/Elev= 30
      10  760.76      20  754.08    40.1  740.88    60.1   728.2    70.1  722.06
    80.2  716.02   100.2  704.32   110.2  698.85   120.2  694.37   130.3  691.71
   135.3   691.3   140.3  690.88   145.3  691.06   150.3  691.24   160.3  691.86
   170.3  692.32   180.4  693.11   200.4  695.22   210.4  696.47   220.4  698.14
   230.5  701.05   240.5  705.17   250.5  709.68   270.5  716.78   280.6  720.57
   310.6  732.85   330.7  741.29   340.7  745.66   350.7  750.17   360.7  755.29
#Mann= 3 , 0 , 0
       0      .1       0   135.3    .045       0   145.3      .1       0
Bank Sta=135.3,145.3
XS Rating Curve= 0 ,0
Exp/Cntr=0.3,0.1

Type RM Length L Ch R = 1 ,4556.4  ,188.2,187,185.8
XS GIS Cut Line= 2
     1572151.269      337899.103      1571463.11      337903.487
#Sta/Elev= 30
    10.1  859.17    40.5  840.63    91.1  804.24   101.2  797.28   111.3  790.79
   131.6  778.81   151.8  767.49     172  756.99   192.3  747.21   222.6  733.68
   273.2  712.26   313.7  695.71   323.8  692.82     334  691.28   344.1  690.47
   379.6  688.97   384.6  688.55   389.6  689.44   394.7  690.34   414.9  701.45
   465.5  725.81   485.8   736.9     506  749.01   526.3  761.98   546.5  775.78
   617.3  826.17   637.6  840.11   667.9  860.26   678.1  866.49   688.2  871.97
#Mann= 3 , 0 , 0
       0      .1       0   379.6    .045       0   389.6      .1       0
Bank Sta=379.6,389.6
XS Rating Curve= 0 ,0
Exp/Cntr=0.3,0.1

Type RM Length L Ch R = 1 ,4369.4  ,156.3,157.9,159.4
XS GIS Cut Line= 2
     1572046.073       337701.86     1571430.236      337734.734
#Sta/Elev= 30
    10.1  796.58    60.7  768.36   111.2  740.85   141.5   725.2     182  705.66
   202.2  697.48   212.3  693.65   222.4  690.26   232.5  687.68   242.6  685.63
   252.8  684.15   257.9  684.02   262.9  683.89   267.9  684.57     273  685.27
   283.1  688.31   313.4  698.56   323.5  702.41   333.6  706.45   343.7  710.93
   353.9  716.02   374.1  726.79   384.2  732.64   394.3  738.99   424.6  758.56
     455  778.71   525.7  826.18   545.9  839.29   576.3  858.55   616.7  884.53
#Mann= 3 , 0 , 0
       0      .1       0   257.9    .045       0   267.9      .1       0
Bank Sta=257.9,267.9
XS Rating Curve= 0 ,0
Exp/Cntr=0.3,0.1

Type RM Length L Ch R = 1 ,4211.5  ,309.8,300.9,292
XS GIS Cut Line= 2
     1572120.587      337570.365     1571493.792      337552.832
#Sta/Elev= 30
    10.1  832.25    30.3  820.84    70.8  799.69   111.2  777.16   141.6  760.84
     182  739.93   222.5  719.85   242.7  711.75   252.8  706.53     263  701.96
   283.2  693.63   293.3  689.78   303.4  686.69   313.5  684.66   318.6  684.23
   323.6  683.82   328.6  684.19   333.7  684.58   343.9  687.95     354   692.8
   364.1  697.17   384.3  705.36   394.4  708.55   404.5  710.02   414.7  712.44
   424.8  717.03   455.1  733.73   475.3  744.13   525.9   768.6     627  816.28
#Mann= 3 , 0 , 0
       0      .1       0   318.6    .045       0   328.6      .1       0
Bank Sta=318.6,328.6
XS Rating Curve= 0 ,0
Exp/Cntr=0.3,0.1

Type RM Length L Ch R = 1 ,3910.6  ,341.5,348.2,354.9
XS GIS Cut Line= 2
     1571978.134      337195.603     1571447.769      337379.696
#Sta/Elev= 30
      10  759.51    60.2   734.1    70.2  729.16   110.3  709.76   120.3     705
   130.3  700.47   140.4   696.2   150.4  691.82   160.4   687.2   170.4  683.41
   180.5  680.83   190.5   678.7   200.5  677.21   205.5  677.02   210.5  676.83
   215.5  677.19   220.6  677.57   270.7  684.61   280.7   685.9   290.7  687.68
   300.8  691.08   310.8   695.6   350.9  714.06     381  728.41     391   733.5
     401  739.07   421.1  751.19   491.2  794.18   531.3  818.19   561.4  835.55
#Mann= 3 , 0 , 0
       0      .1       0   205.5    .045       0   215.5      .1       0
Bank Sta=205.5,215.5
XS Rating Curve= 0 ,0
Exp/Cntr=0.3,0.1

Type RM Length L Ch R = 1 ,3562.4  ,239.7,225,210.3
XS GIS Cut Line= 2
     1571956.218      336932.612     1571346.955      336974.252
#Sta/Elev= 30
      10  795.01      40  777.42    60.1  766.25    70.1  760.74    90.1  751.13
   100.1  745.13   130.1  728.69   210.2  682.28   220.2  677.75   230.3  675.45
   280.3  671.05   295.3  669.35   300.3  668.88   305.3  668.97   310.3  669.06
   320.4  671.39   350.4  680.39   360.4  684.11   370.4  688.58   380.4  693.78
   390.4  699.62   420.5   718.1   430.5  723.74   470.5  744.28   490.5  753.51
   510.6  762.06   570.6  785.84   590.7  794.13   600.7  798.79   610.7  804.22
#Mann= 3 , 0 , 0
       0     .08       0   295.3    .045       0   305.3     .08       0
Bank Sta=295.3,305.3
XS Rating Curve= 0 ,0
Exp/Cntr=0.3,0.1

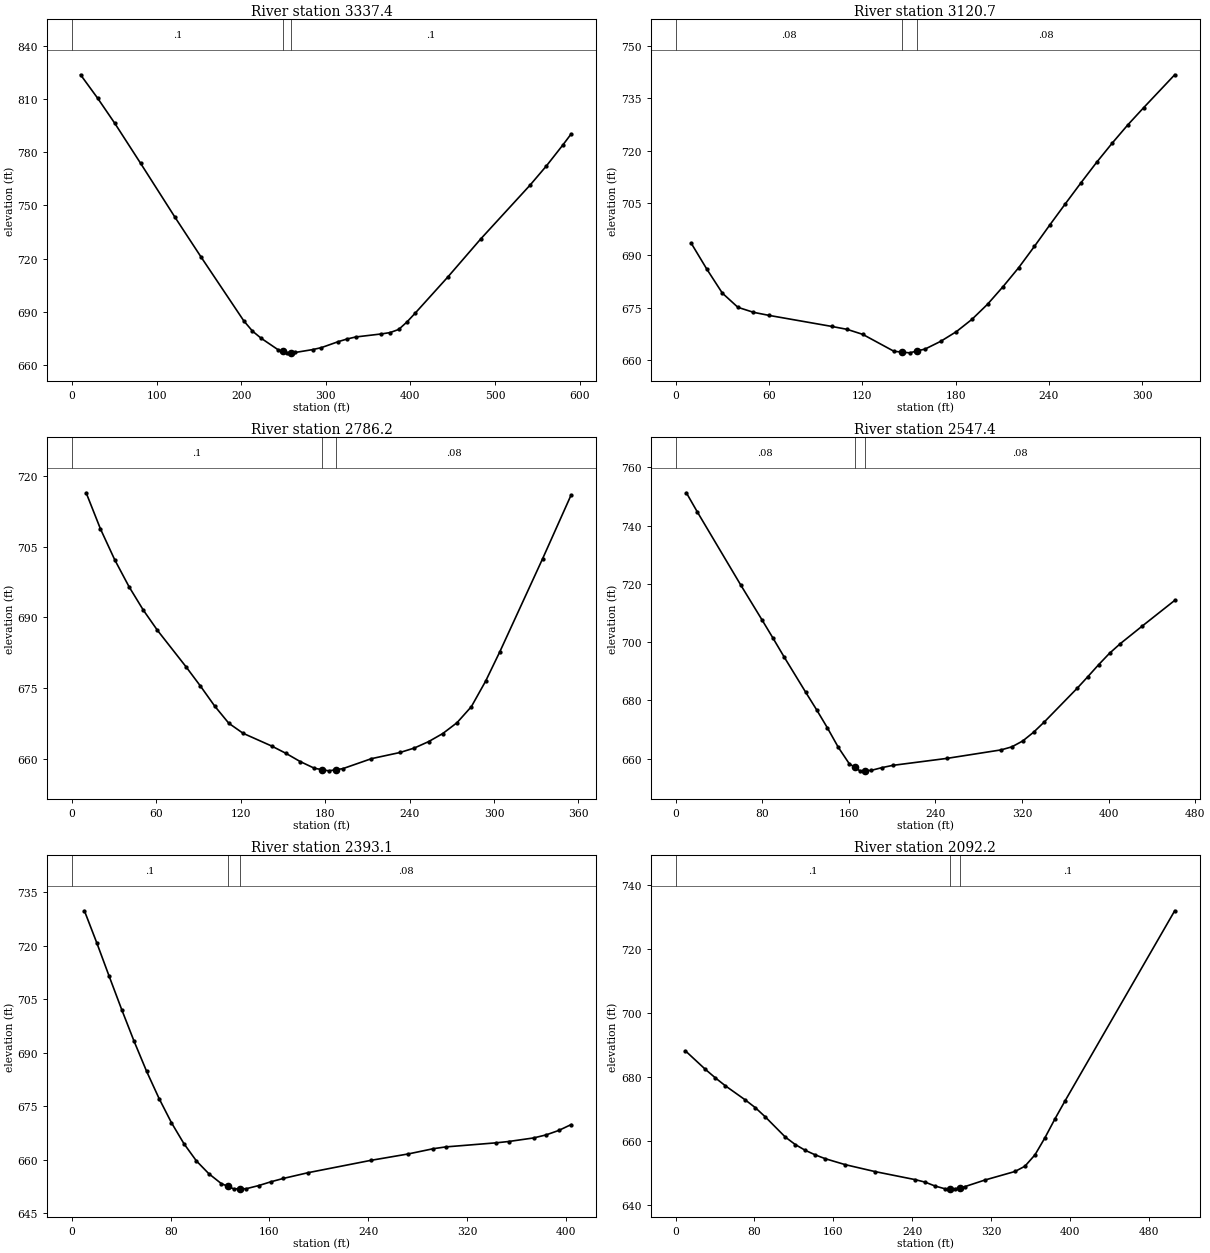
Type RM Length L Ch R = 1 ,3337.4  ,219.8,216.7,213.7
XS GIS Cut Line= 3
     1571818.148      336577.574     1571511.325      336812.075
     1571346.955      336932.612
#Sta/Elev= 30
    10.2  823.76    30.5  810.47    50.8  796.27    81.3   773.7   121.9  743.29
   152.4  721.08   203.2  684.85   213.4  679.11   223.6   675.1   243.9  668.52
   249.1  667.67   254.1  666.85   259.1  666.96   264.2  667.08   284.5  668.68
   294.7  669.77     315   673.2   325.2  674.66   335.4   675.8   365.8  677.52
     376  678.28   386.2  680.05   395.9  684.23   405.6  689.19   444.4  709.71
   483.2  731.14   541.5   761.5   560.9  772.39   580.3  784.18     590  790.34
#Mann= 3 , 0 , 0
       0      .1       0   249.1    .045       0   259.1      .1       0
Bank Sta=249.1,259.1
XS Rating Curve= 0 ,0
Exp/Cntr=0.3,0.1

Type RM Length L Ch R = 1 ,3120.7  ,326.3,334.4,342.6
XS GIS Cut Line= 2
     1571550.773      336496.485     1571320.656      336720.028
#Sta/Elev= 29
      10  693.53    20.1  686.06    30.1  679.18    40.1  675.12    50.1  673.69
    60.2   672.8   100.3  669.66   110.3  668.81   120.3  667.38   140.4  662.53
   145.4  662.31   150.4  662.09   155.4  662.64   160.4  663.18   170.4  665.38
   180.5  668.16   190.5  671.68   200.5  675.99   210.5  681.05   220.6  686.51
   230.6  692.54   240.6  698.74   250.6  704.81   260.7  710.85   270.7  716.67
   280.7  722.16   290.7  727.37   300.8  732.25   320.8  741.69
#Mann= 3 , 0 , 0
       0     .08       0   145.4    .045       0   155.4     .08       0
Bank Sta=145.4,155.4
XS Rating Curve= 0 ,0
Exp/Cntr=0.3,0.1

Type RM Length L Ch R = 1 ,2786.2  ,234.2,238.8,243.3
XS GIS Cut Line= 2
     1571428.044      336242.261     1571108.072      336395.672
#Sta/Elev= 30
    10.1   716.5    20.3   708.8    30.4  702.27    40.6  696.53    50.7  691.58
    60.8  687.26    81.1  679.52    91.2  675.48   101.4   671.2   111.5  667.52
   121.7  665.38   141.9  662.69   152.1  661.13   162.2  659.39   172.4  657.95
   177.5  657.68   182.5  657.41   187.5  657.64   192.6  657.88   212.9     660
   233.2  661.31   243.3  662.25   253.5  663.62   263.6  665.34   273.7  667.64
   283.9  671.05     294  676.45   304.2  682.76   334.6  702.53   354.8  716.03
#Mann= 3 , 0 , 0
       0      .1       0   177.5    .045       0   187.5     .08       0
Bank Sta=177.5,187.5
XS Rating Curve= 0 ,0
Exp/Cntr=0.3,0.1

Type RM Length L Ch R = 1 ,2547.4  ,150.7,154.3,157.9
XS GIS Cut Line= 2
      1571366.68      336047.209     1570921.969       336168.96
#Sta/Elev= 30
      10  751.26      20  744.77    60.1  719.68    80.2  707.44    90.2  701.26
   100.2  694.97   120.3  682.75   130.3  676.78   140.3  670.55   150.4  663.85
   160.4  658.29   165.4  657.04   170.4   655.8   175.4  655.86   180.4  655.92
   190.4  656.88   200.5  657.67   250.6  660.07   300.7  662.99   310.7  664.04
   320.7  666.05   330.8  669.07   340.8  672.64   370.9  684.11   380.9  688.14
   390.9  692.27   400.9  696.16     411  699.51     431  705.47   461.1  714.31
#Mann= 3 , 0 , 0
       0     .08       0   165.4    .045       0   175.4     .08       0
Bank Sta=165.4,175.4
XS Rating Curve= 0 ,0
Exp/Cntr=0.3,0.1

Type RM Length L Ch R = 1 ,2393.1  ,293.1,300.9,308.7
XS GIS Cut Line= 3
     1571305.763      335924.412     1571075.714      335952.998
     1570910.632       335902.97
#Sta/Elev= 30
    10.1  729.74    20.2  720.69    30.2  711.36    40.3  702.08    50.4  693.15
    60.5  684.77    70.6  677.16    80.6   670.4    90.7  664.53   100.8   659.7
   110.9  656.11   120.9  653.37     126  652.62     131  651.88     136   651.9
   141.1  651.91   151.2  652.79   161.3  653.87   171.3   654.8   191.5  656.42
     242  659.85   272.4  661.65   292.7  663.12   302.8  663.62   343.4  664.76
   353.6  665.13   373.9  666.13     384  666.98   394.2  668.22   404.3  669.87
#Mann= 3 , 0 , 0
       0      .1       0     126    .045       0     136     .08       0
Bank Sta=126,136
XS Rating Curve= 0 ,0
Exp/Cntr=0.3,0.1

Type RM Length L Ch R = 1 ,2092.2  ,282,288.7,295.4
XS GIS Cut Line= 2
     1571434.619      335694.363     1570937.128      335600.125
#Sta/Elev= 30
    10.1  688.11    30.4  682.32    40.5  679.67    50.6  677.21    70.9  672.77
      81  670.37    91.1  667.49   111.4  661.19   121.5  658.86   131.6  657.06
   141.8  655.63   151.9  654.44   172.2  652.58   202.5  650.41     243  647.91
   253.2  647.12   263.3   645.9   273.4  645.04   278.5  645.04   283.5  645.03
   288.5  645.38   293.7  645.75   313.9  647.79   344.3  650.45   354.4   652.1
   364.6  655.66   374.7  660.99   384.8  666.86   394.9  672.41   506.3  731.89
#Mann= 3 , 0 , 0
       0      .1       0   278.5    .045       0   288.5      .1       0
Bank Sta=278.5,288.5
XS Rating Curve= 0 ,0
Exp/Cntr=0.3,0.1

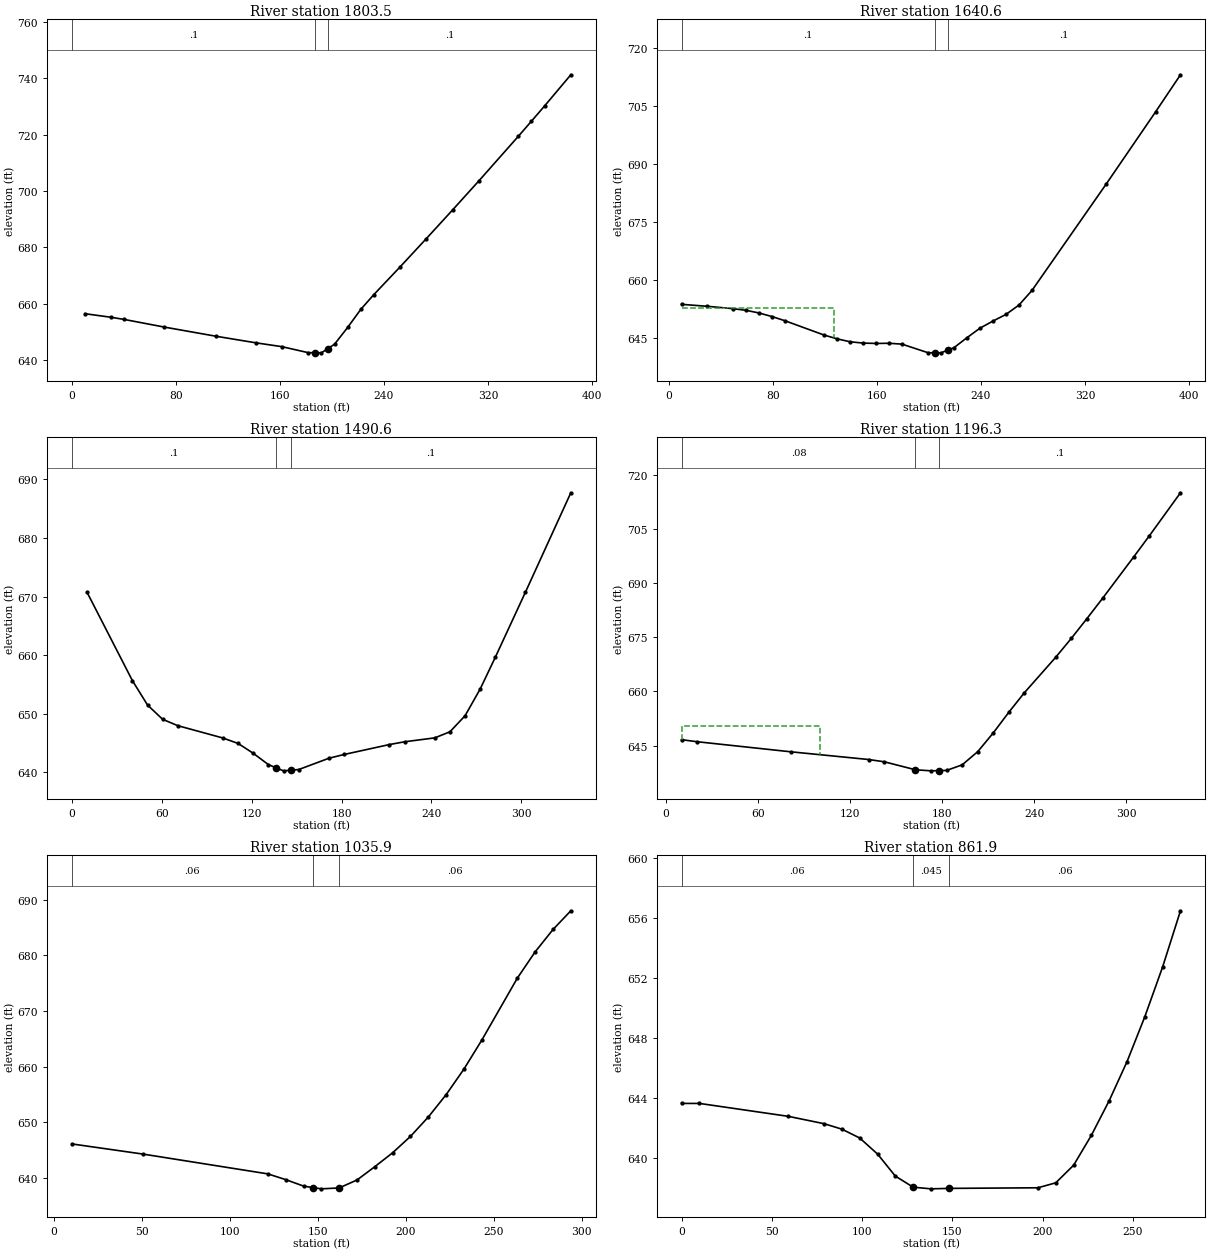
Type RM Length L Ch R = 1 ,1803.5  ,160.6,162.9,165.3
XS GIS Cut Line= 2
     1571442.885       335462.14     1571098.022      335293.595
#Sta/Elev= 23
    10.1  656.37    30.3  655.09    40.4  654.32    70.7  651.65   111.1  648.34
   141.4  646.03   161.6  644.65   181.8  642.52   186.9  642.49   191.9  642.46
   196.9  643.97     202  645.51   212.1  651.48   222.2   657.9   232.3  663.18
   252.5  673.03   272.7  683.09   292.9  693.29   313.1  703.61   343.4  719.43
   353.5   724.8   363.6  730.22   383.8  741.31
#Mann= 3 , 0 , 0
       0      .1       0   186.9    .045       0   196.9      .1       0
Bank Sta=186.9,196.9
XS Rating Curve= 0 ,0
Exp/Cntr=0.3,0.1

Type RM Length L Ch R = 1 ,1640.6  ,164.2,150,135.8
XS GIS Cut Line= 4
      1571504.64      335383.843      1571452.81      335298.931
     1571299.526      335205.196     1571185.941      335194.168
#Sta/Elev= 28
     9.9  653.64    29.8  653.13    49.7  652.51    59.7  652.08    69.6  651.39
    79.6  650.46    89.5  649.38   119.4   645.7   129.4  644.72   139.4  643.96
   149.4  643.62   159.4  643.53   169.4  643.57   179.3  643.35   199.3  641.13
   204.3  641.11   209.3   641.1   214.3  641.78   219.3  642.45   229.2  645.01
   239.2  647.47   249.2  649.32   259.2  651.03   269.2  653.46   279.2  657.24
   336.2  684.73   374.3  703.47   393.3  712.99
#Mann= 3 , 0 , 0
     9.9      .1       0   204.3    .045       0   214.3      .1       0
#XS Ineff= 2 , 0
          127.07  652.74
Permanent Ineff=
       F       F
Bank Sta=204.3,214.3
XS Rating Curve= 0 ,0
Exp/Cntr=0.3,0.1

Type RM Length L Ch R = 1 ,1490.6  ,293.5,294.2,295
XS GIS Cut Line= 2
     1571574.881        335111.4     1571241.759      335113.592
#Sta/Elev= 24
    10.1  670.72    40.4  655.63    50.5  651.47    60.6  649.03    70.7  647.95
   100.9  645.84     111  644.91   121.1  643.23   131.2   641.3   136.3  640.76
   141.3  640.24   146.3  640.35   151.4  640.46   171.6  642.39   181.7  643.03
     212  644.73   222.1   645.2   242.3  645.87   252.4  646.91   262.5  649.65
   272.6  654.22   282.7  659.64   302.8  670.74   333.1  687.71
#Mann= 3 , 0 , 0
       0      .1       0   136.3    .045       0   146.3      .1       0
Bank Sta=136.3,146.3
XS Rating Curve= 0 ,0
Exp/Cntr=0.3,0.1

Type RM Length L Ch R = 1 ,1196.3  ,160.8,160.4,160
XS GIS Cut Line= 2
     1571552.965       334835.26     1571217.652      334828.685
#Sta/Elev= 21
    10.2  646.63    20.3  646.07    81.3  643.28   132.1  641.14   142.3  640.51
   162.6   638.3   172.8     638   177.8  638.06   182.9  638.11   193.1  639.66
   203.3  643.34   213.4  648.53   223.6  654.28   233.7  659.67   254.1  669.48
   264.2  674.68   274.4  680.17   284.6  685.79   304.9  697.27   315.1  703.12
   335.4  715.05
#Mann= 3 , 0 , 0
    10.2     .08       0   162.6    .045       0   177.8      .1       0
#XS Ineff= 2 , 0
          100.35  650.41
Permanent Ineff=
       F       F
Bank Sta=162.6,177.8
XS Rating Curve= 0 ,0
Exp/Cntr=0.3,0.1

Type RM Length L Ch R = 1 ,1035.9  ,166.7,174.1,181.7
XS GIS Cut Line= 2
     1571561.731      334675.273     1571268.058      334673.082
#Sta/Elev= 20
    10.1  646.07    50.6  644.24   121.5  640.68   131.7  639.64   141.8  638.48
   146.9  638.23   151.9  637.99     162  638.15   172.2  639.59   182.3  641.98
   192.4  644.48   202.5  647.41   212.7  650.92   222.8  654.93   232.9  659.52
     243   664.7   263.3  675.91   273.4  680.63   283.6  684.67   293.7  688.03
#Mann= 3 , 0 , 0
    10.1     .06       0   146.9    .045       0     162     .06       0
Bank Sta=146.9,162
XS Rating Curve= 0 ,0
Exp/Cntr=0.3,0.1

Type RM Length L Ch R = 1 ,861.9   ,81.8,81.3,80.3
XS GIS Cut Line= 2
     1571614.585      334560.761     1571351.404      334476.371
#Sta/Elev= 20
       0  643.65     9.9  643.65    59.2  642.79      79   642.3    88.8  641.94
    98.7  641.35   108.6  640.28   118.4  638.82   128.3  638.08   138.2  637.97
   148.1     638   197.4  638.04   207.3  638.37   217.2  639.54     227  641.52
   236.9  643.83   246.8  646.43   256.6   649.4   266.5  652.72   276.4  656.46
#Mann= 3 , 0 , 0
       0     .06       0   128.3    .045       0   148.1     .06       0
Bank Sta=128.3,148.1
XS Rating Curve= 0 ,0
Exp/Cntr=0.3,0.1

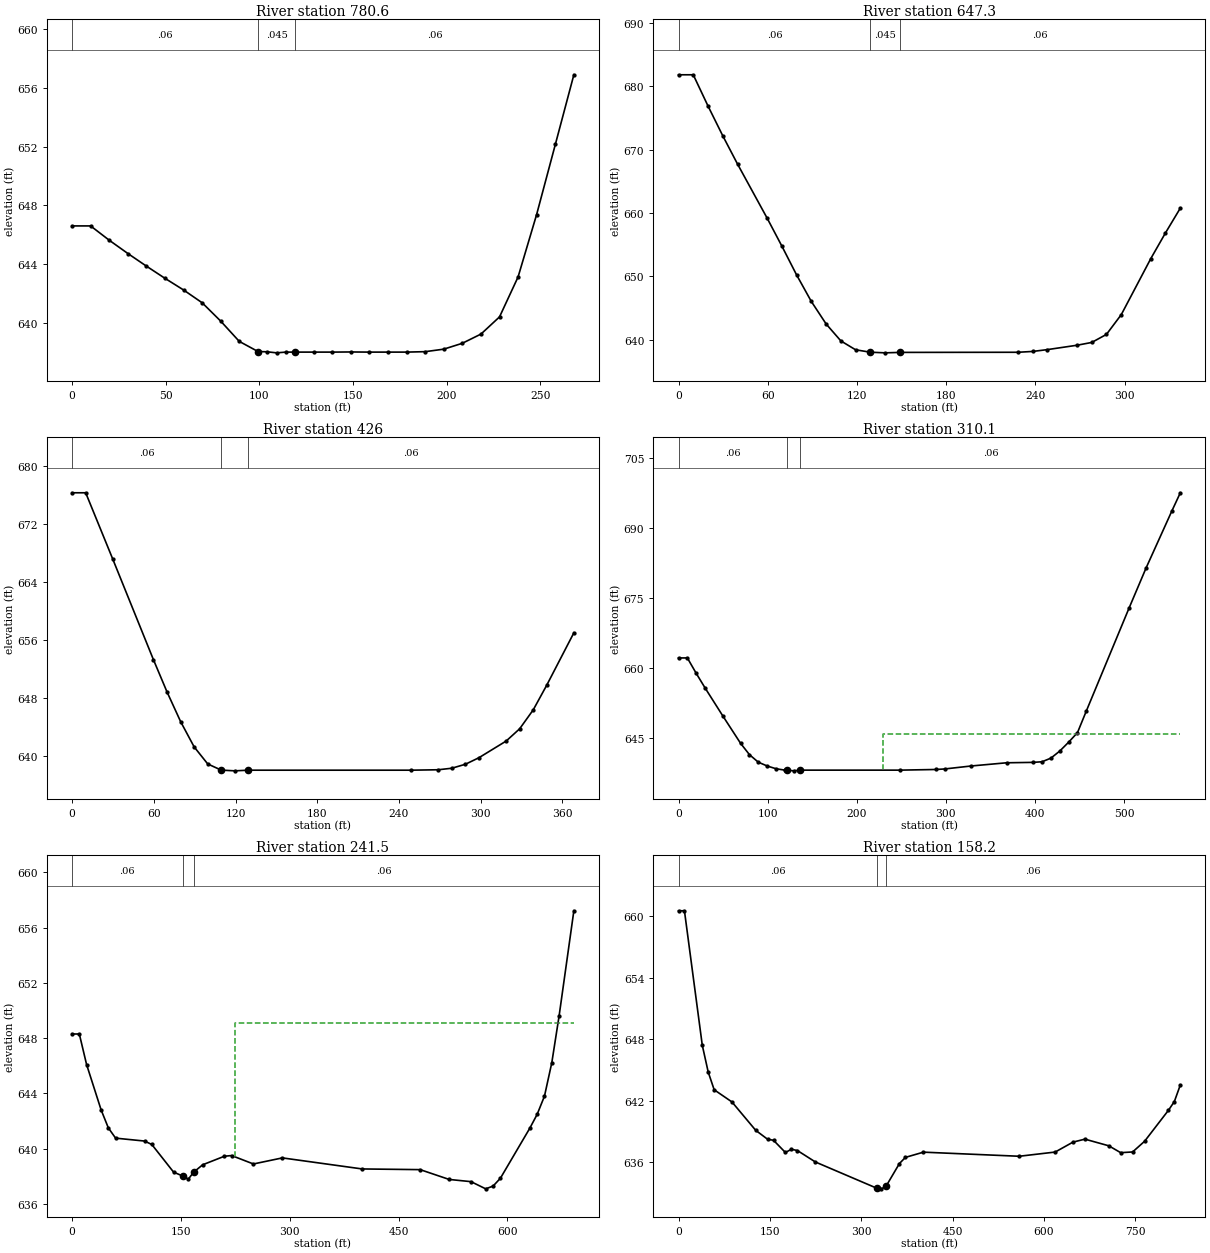
Type RM Length L Ch R = 1 ,780.6   ,142.6,133.3,124.3
XS GIS Cut Line= 2
     1571631.749      334482.093     1571374.289      334407.716
#Sta/Elev= 30
       0   646.6     9.9   646.6    19.9  645.62    29.8  644.72    39.7  643.86
    49.6  643.03    59.6  642.23    69.5  641.36    79.4  640.11    89.3  638.73
    99.3  638.04   104.2  638.02   109.2  637.95   114.2     638   119.1     638
     129     638     139     638   148.9  638.01   158.8     638   168.7     638
   178.7     638   188.6  638.03   198.5   638.2   208.4   638.6   218.4  639.23
   228.3   640.4   238.2  643.12   248.1  647.37   258.1  652.15     268   656.9
#Mann= 3 , 0 , 0
       0     .06       0    99.3    .045       0   119.1     .06       0
Bank Sta=99.3,119.1
XS Rating Curve= 0 ,0
Exp/Cntr=0.3,0.1

Type RM Length L Ch R = 1 ,647.3   ,225.5,221.3,217.1
XS GIS Cut Line= 2
     1571693.254      334311.883     1571357.125       334341.92
#Sta/Elev= 25
       0  681.85     9.9  681.85    19.9  676.88    29.8  672.19    39.7  667.74
    59.6   659.2    69.5  654.79    79.4  650.24    89.3  646.05    99.3  642.48
   109.2  639.81   119.1  638.41     129  638.03     139  637.93   148.9     638
   228.3  638.02   238.2  638.15   248.1  638.44     268  639.13   277.9  639.57
   287.8  640.84   297.8  643.97   317.6   652.8   327.5  656.87   337.5  660.79
#Mann= 3 , 0 , 0
       0     .06       0     129    .045       0   148.9     .06       0
Bank Sta=129,148.9
XS Rating Curve= 0 ,0
Exp/Cntr=0.3,0.1

Type RM Length L Ch R = 1 ,426     ,114.7,115.9,117
XS GIS Cut Line= 2
      1571612.78      334081.367     1571256.261      334174.371
#Sta/Elev= 21
       0  676.27      10  676.27    29.9  667.11    59.7  653.26    69.7   648.8
    79.7   644.7    89.6  641.22    99.6  638.86   109.5  638.01   119.5  637.91
   129.5     638     249     638   268.9  638.06   278.8  638.27   288.8  638.82
   298.7  639.72   318.7  642.02   328.6  643.71   338.6  646.33   348.5  649.73
   368.4  656.95
#Mann= 3 , 0 , 0
       0     .06       0   109.5    .045       0   129.5     .06       0
Bank Sta=109.5,129.5
XS Rating Curve= 0 ,0
Exp/Cntr=0.3,0.1

Type RM Length L Ch R = 1 ,310.1   ,66.1,68.6,70.9
XS GIS Cut Line= 3
     1571597.279      333972.861      1571159.14      334065.101
     1571110.252      334169.571
#Sta/Elev= 30
       0   662.1     9.9   662.1    19.9  658.77    29.8  655.65    49.7  649.64
    69.6  643.77    79.6  641.32    89.5  639.71    99.5  638.89   109.4   638.3
   119.4     638   121.8     638   129.1  637.85   136.8     638   248.7     638
   288.5  638.14   298.5  638.25   328.3  638.89   368.1  639.58     398  639.67
   407.9   639.8   417.9  640.58   427.8   642.1   437.8  644.01   447.7  646.06
   457.4   650.6   505.4  672.73   524.6  681.39   553.5  693.62   563.1  697.57
#Mann= 3 , 0 , 0
       0     .06       0   121.8    .045       0   136.8     .06       0
#XS Ineff= 2 , 0
                          229.03          645.85
Permanent Ineff=
       F       F
Bank Sta=121.8,136.8
XS Rating Curve= 0 ,0
Exp/Cntr=0.3,0.1

Type RM Length L Ch R = 1 ,241.5   ,90.9,83.3,75.9
XS GIS Cut Line= 3
     1571593.323      333937.142     1571053.636      333937.535
     1570910.702      333988.583
#Sta/Elev= 30
       0   648.3      10   648.3      20  646.09      40  642.81      50   641.5
      60  640.76    99.9  640.55   109.9   640.3   139.9   638.3   152.4  638.02
  160.25  637.79   167.4  638.29   179.9  638.83   209.9  639.45   219.9   639.5
   249.9  638.89   289.8  639.33   399.8  638.53   479.7  638.48   519.7  637.77
   549.8  637.61     570  637.09   580.2  637.29   590.3  637.86   630.8  641.48
   640.9  642.48     651   643.8   661.1  646.22   671.2  649.62   691.5  657.22
#Mann= 3 , 0 , 0
       0     .06       0   152.4    .045       0   167.4     .06       0
#XS Ineff= 2 , 0
                          223.86           649.1
Permanent Ineff=
       F       F
Bank Sta=152.4,167.4
XS Rating Curve= 0 ,0
Exp/Cntr=0.3,0.1

Type RM Length L Ch R = 1 ,158.2   ,63.2,58.8,54.5
XS GIS Cut Line= 5
     1571714.011      333937.142     1571564.659      333845.117
     1571309.684      333869.021     1571125.103      333896.697
     1570932.049      333967.236
#Sta/Elev= 30
       0  660.52     9.7  660.52      39  647.39    48.7  644.78    58.5  643.05
    87.7  641.86   126.7  639.09   146.2  638.22   155.9  638.12   175.4  636.93
   185.3  637.24   195.1  637.12   224.7     636   325.5  633.44     333  633.38
   340.5  633.62   362.6  635.85   372.4  636.45     402  636.96   559.2  636.56
   618.2  636.97   647.5  637.94   667.1  638.23   706.3  637.58   725.8  636.91
   745.4  636.98     765  638.02   804.1  641.04   813.9   641.9   823.7  643.52
#Mann= 3 , 0 , 0
       0     .06       0   325.5    .045       0   340.5     .06       0
Bank Sta=325.5,340.5
XS Rating Curve= 0 ,0
Exp/Cntr=0.3,0.1

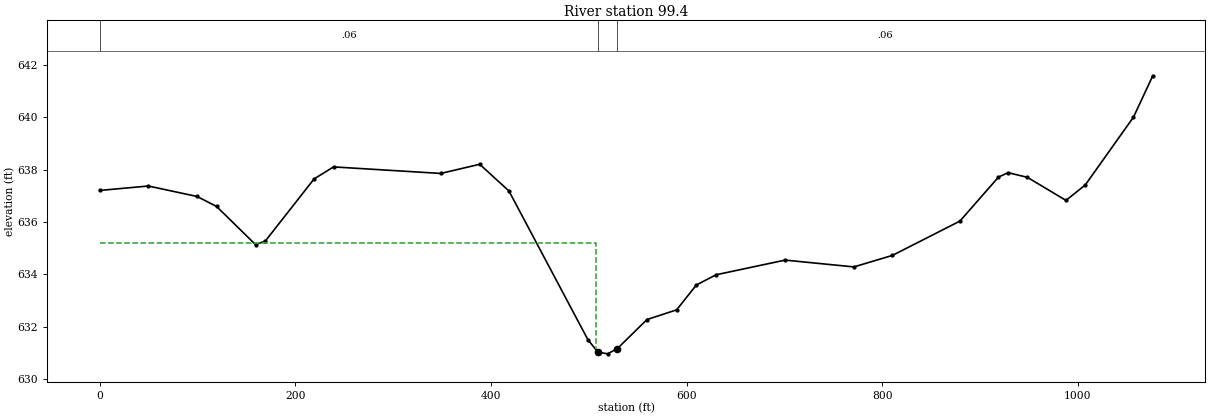
Type RM Length L Ch R = 1 ,99.4    ,99.1,99.3,99.6
XS GIS Cut Line= 4
     1571964.438      333820.979     1571551.082       333756.11
     1571222.207       333852.66     1570923.504      333953.736
#Sta/Elev= 30
       0   637.2    49.8  637.37    99.6  636.97   119.5  636.59   159.4  635.13
   169.4  635.27   219.2  637.64   239.1   638.1   348.7  637.85   388.5   638.2
   418.4  637.18   499.1   631.5   509.2  631.03   519.2  630.96   529.2  631.16
   559.5  632.27   589.8  632.64     610  633.59   630.1  633.98   700.7  634.54
     771  634.28   810.4  634.72   879.4  636.03   918.8  637.71   928.7  637.88
   948.4   637.7   987.8  636.82  1007.5  637.41  1056.8     640  1076.5  641.58
#Mann= 3 , 0 , 0
       0     .06       0   509.2    .045       0   529.2     .06       0
#XS Ineff= 2 , 0
          507.11  635.18
Permanent Ineff=
       F       F
Bank Sta=509.2,529.2
XS Rating Curve= 0 ,0
Exp/Cntr=0.3,0.1

Chan Stop Cuts=-1
Use User Specified Reach Order=0